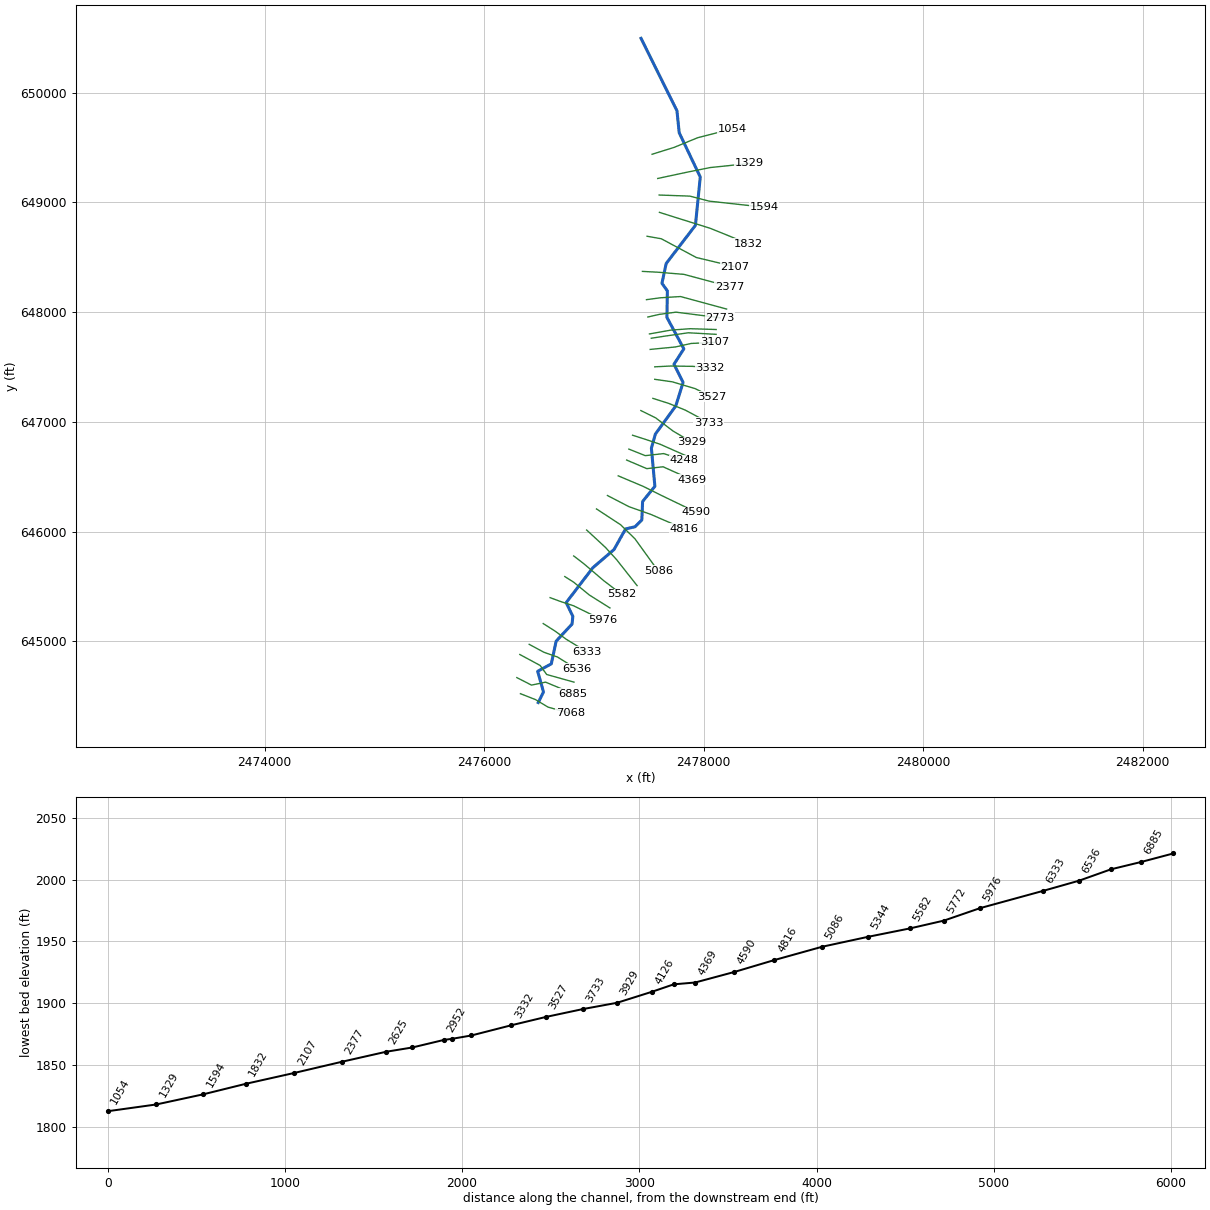
--- JOHNSONRN.prj (project) ---

Proj Title=JOHNSONRN
Current Plan=p01
Default Exp/Contr=0,0
English Units
Geom File=g01
Flow File=f01
Plan File=p01
Background Map Layer=QC
BEGIN DESCRIPTION:
Stream Name:Johnson Run
Flood Zone: Zone A
Pendleton County, WV
WVDHSEM Flood Warning & Analysis Mapping
HEC-RAS Version: 5.0.7
Hydrology Method:
Regression
Model Notes:
Tie in with Mill Run at the downstream end.
END DESCRIPTION:
DSS Export Rating Curves= 0
DSS Export Rating Curve Sorted= 0
DSS Export Volume Flow Curves= 0
DXF OffsetX= 0
DXF OffsetY= 0
DXF ScaleX= 0
DXF ScaleY= 0

--- JOHNSONRN.p01 (plan) ---

Plan Title=Floodplain
Program Version=5.07
Short Identifier=Floodplain
Geom File=g01
Flow File=f01
Subcritical Flow
K Sum by GR= 0
Std Step Tol= 0.01
Critical Tol= 0.01
Num of Std Step Trials= 20
Max Error Tol= 0.3
Flow Tol Ratio= 0.001
Split Flow NTrial= 30
Split Flow Tol= 0.02
Split Flow Ratio= 0.02
Log Output Level= 0
Friction Slope Method= 1
Unsteady Friction Slope Method= 2
Unsteady Bridges Friction Slope Method= 1
Parabolic Critical Depth
Global Vel Dist= 0 , 0 , 0
Global Log Level= 0
CheckData=True
Encroach Param=-1 ,0,0, 0
Mapping Interval=1HOUR
Computation Time Step Use Courant=        0
Computation Time Step Use Time Series=    0
Computation Time Step Count To Double=0
Computation Time Step Max Doubling=0
Computation Time Step Max Halving=0
Computation Time Step Residence Courant=0
Run HTab= 0
Run UNet= 0
Run Sediment= 0
Run PostProcess= 0
Run WQNet= 0
Run RASMapper= 0
UNET Theta= 0
UNET Theta Warmup= 0
UNET ZTol= 0
UNET ZSATol= 0
UNET MxIter= 0
UNET Max Iter WO Improvement= 0
UNET MaxInSteps= 0
UNET DtIC= 0
UNET DtMin= 0
UNET MaxCRTS= 0
UNET WFStab= 0
UNET SFStab= 0
UNET WFX= 1
UNET SFX= 1
UNET 1D Methodology=Finite Difference
UNET DSS MLevel= 1
UNET Pardiso=0
UNET DZMax Abort= 0
UNET Use Existing IB Tables= 0
UNET Froude Reduction=False
UNET Froude Limit= 0
UNET Froude Power= 0
UNET D1 Cores= 0
UNET D2 Coriolis=0
UNET D2 Cores= 0
UNET D2 Theta= 1
UNET D2 Theta Warmup= 1
UNET D2 Z Tol= 0.01
UNET D2 Volume Tol= 0.01
UNET D2 Max Iterations= 20
UNET D2 Equation= 0
UNET D2 RampUpFraction=0.1
UNET D2 TimeSlices= 1
UNET D2 BCVolumeCheck=0
UNET D1D2 MaxIter= 0
UNET D1D2 ZTol=0.01
UNET D1D2 QTol=0.1
UNET D1D2 MinQTol=1
Write IC File= 0
Write IC File at Fixed DateTime=0
Write IC File at Sim End=0
Echo Input=False
Echo Parameters=False
Echo Output=False
Write Detailed= 0
HDF Write Warmup=0
HDF Write Time Slices=0
HDF Flush=0
HDF Face Node Velocities=0
HDF Compression= 1
HDF Chunk Size= 1
HDF Spatial Parts= 1
HDF Use Max Rows=0
HDF Fixed Rows= 1
Calibration Method= 0
Calibration Iterations= 20
Calibration Max Change=0.05
Calibration Tolerance=0.2
Calibration Maximum=1.5
Calibration Minimum=0.5
Calibration Optimization Method= 1
WQ AD Non Conservative
WQ ULTIMATE=-1
WQ Max Comp Step=1HOUR
WQ Output Interval=15MIN
WQ Output Selected Increments= 0
WQ Output face flow=0
WQ Output face velocity=0
WQ Output face area=0
WQ Output face dispersion=0
WQ Output cell volume=0
WQ Output cell surface area=0
WQ Output cell continuity=0
WQ Output cumulative cell continuity=0
WQ Output face conc=0
WQ Output face dconc_dx=0
WQ Output face courant=0
WQ Output face peclet=0
WQ Output face adv mass=0
WQ Output face disp mass=0
WQ Output cell mass=0
WQ Output cell source sink temp=0
WQ Output nsm pathways=0
WQ Output nsm derived pathways=0
WQ Output MaxMinRange=-1
WQ Daily Max Min Mean=-1
WQ Daily Range=0
WQ Daily Time=0
WQ Create Restart=0
WQ Fixed Restart=0
WQ System Summary=0
WQ Write To DSS=0
WQ Use Fixed Temperature=0
Sorting and Armoring Iterations= 10
XS Update Threshold= 0.02
Bed Roughness Predictor= 0
Hydraulics Update Threshold= 0.02
Energy Slope Method= 1
Volume Change Method= 1
Sediment Retention Method= 0
XS Weighting Method= 0
Number of US Weighted Cross Sections= 1
Number of DS Weighted Cross Sections= 1
Upstream XS Weight=0
Main XS Weight=1
Downstream XS Weight=0
Number of DS XS's Weighted with US Boundary= 1
Upstream Boundary Weight= 1
Weight of XSs Associated with US Boundary= 0
Number of US XS's Weighted with DS Boundary= 1
Downstream Boundary Weight= 0.5
Weight of XSs Associated with DS Boundary= 0.5
Percentile Method= 0
Sediment Output Level= 3
Mass or Volume Output= 0
Output Increment Type= 1
Profile and TS Output Increment= 1
XS Output Flag= 0
XS Output Increment= 10
Write Gradation File= 0
Read Gradation Hotstart= 0
Write HDF5 File= 1
Write Binary Output= 1
Write DSS Sediment File= 0
SV Curve= 0
Specific Gage Flag= 0

--- JOHNSONRN.f01 (steady flow) ---

Flow Title=Flows
Program Version=5.07
Number of Profiles= 6
Profile Names=P100yr,P10yr,P25yr,P50yr,P500yr,P101yr
River Rch & RM=JOHNSONRN,Main            ,7068
     585     274     387     483     858     712
River Rch & RM=JOHNSONRN,Main            ,5344
     652     305     431     538     958     794
River Rch & RM=JOHNSONRN,Main            ,3527
     732     341     483     603    1075     890
Boundary for River Rch & Prof#=JOHNSONRN,Main            , 1
Up Type= 0
Dn Type= 3
Dn Slope=0.02549
Boundary for River Rch & Prof#=JOHNSONRN,Main            , 2
Up Type= 0
Dn Type= 3
Dn Slope=0.02549
Boundary for River Rch & Prof#=JOHNSONRN,Main            , 3
Up Type= 0
Dn Type= 3
Dn Slope=0.02549
Boundary for River Rch & Prof#=JOHNSONRN,Main            , 4
Up Type= 0
Dn Type= 3
Dn Slope=0.02549
Boundary for River Rch & Prof#=JOHNSONRN,Main            , 5
Up Type= 0
Dn Type= 3
Dn Slope=0.02549
Boundary for River Rch & Prof#=JOHNSONRN,Main            , 6
Up Type= 0
Dn Type= 3
Dn Slope=0.02549
DSS Import GetInterval= 0
DSS Import GetPeak= 0
DSS Import FillOption= 0

--- JOHNSONRN.g01 (geometry) ---

Geom Title=Geometry
Program Version=5.07

River Reach=JOHNSONRN       ,Main
Reach XY= 30
      2476493.23      644441.459     2476540.965      644538.221
     2476488.039      644726.629     2476612.179       644794.26
     2476656.345      645001.151     2476801.521       645157.21
     2476808.422      645227.591     2476747.704      645352.293
     2476990.397      645669.932     2477183.989      645836.276
     2477289.033      646023.761     2477374.511      646043.507
     2477437.362      646105.066     2477444.229       646273.97
     2477556.148      646412.395      2477524.35      646760.191
     2477560.689       646888.51     2477746.413      647144.338
     2477813.281      647358.944     2477730.276      647524.846
     2477819.921      647664.977     2477665.834      647951.783
      2477669.96      648193.332     2477620.563      648262.438
     2477658.968      648442.433     2477925.641      648790.712
     2477969.743      649231.091     2477777.861      649634.451
     2477757.288      649834.705     2477429.893      650494.852

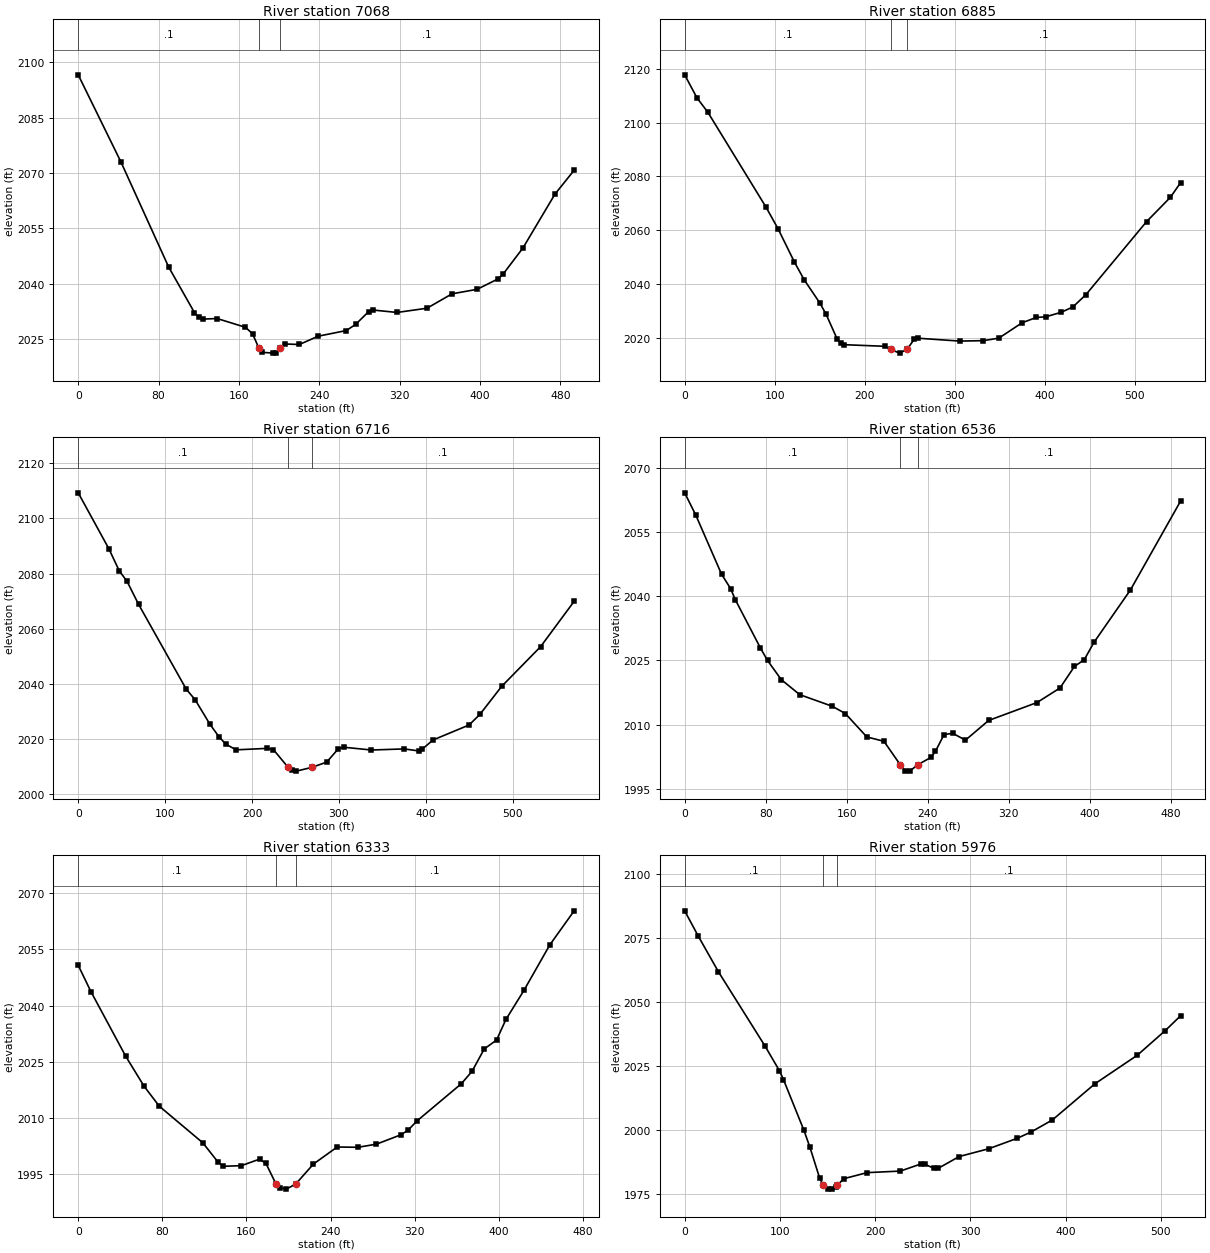
Type RM Length L Ch R = 1 ,7068    ,178.3,182.8,192.8
XS GIS Cut Line= 4
2476330.97923163644522.3630966442476469.03695128644468.278629152
 2476582.8989881644399.9614070572476787.85065439644343.030388645
#Sta/Elev= 30
       0 2096.62    42.7  2072.9      90 2044.53   115.7 2032.16     120 2030.88
   124.3 2030.38   138.3 2030.53   166.5 2028.16   173.6 2026.39  179.992022.439
   182.9 2021.37   194.3 2021.15   196.9 2021.18  200.922022.438   206.2 2023.63
   220.2 2023.49   238.9 2025.74   266.9 2027.27   276.2 2028.93   289.2 2032.42
   293.4 2032.84   317.5 2032.18   347.3 2033.33   372.2 2037.23   397.1 2038.45
   417.9 2041.26     423 2042.56   442.8 2049.66   474.7 2064.27   493.8 2070.75
#Mann= 3 ,-1 , 0
       0      .1       0  179.99    .045       0  200.92      .1       0
Bank Sta=179.99,200.92
XS Rating Curve= 0 ,0
Exp/Cntr(USF)=0,0
Exp/Cntr=0.3,0.1

Type RM Length L Ch R = 1 ,6885    ,176,169.3,149.8
XS GIS Cut Line= 4
2476298.24389604644668.9604690562476432.03178931644600.643246961
2476560.12658074644627.6854807072476809.19978629644523.786372104
#Sta/Elev= 30
       0 2117.85    13.8 2109.19    25.7 2103.93    90.4 2068.55   103.9 2060.41
   121.8 2048.19   132.7 2041.54   150.2 2032.84   157.1 2028.68   169.3 2019.51
   173.4 2017.87   177.5 2017.33   222.5 2016.73  228.932015.578   238.8 2014.19
  247.022015.581   255.2 2019.42   259.3 2019.74   305.6 2018.68   331.7 2018.83
     349 2019.77     375 2025.52   390.8 2027.49     401  2027.7   418.4 2029.41
   431.3 2031.39   445.8 2035.97   513.1 2063.15   539.7 2072.25     551  2077.7
#Mann= 3 ,-1 , 0
       0      .1       0  228.93    .045       0  247.02      .1       0
Bank Sta=228.93,247.02
XS Rating Curve= 0 ,0
Exp/Cntr(USF)=0,0
Exp/Cntr=0.3,0.1

Type RM Length L Ch R = 1 ,6716    ,175.5,180,188.2
XS GIS Cut Line= 4
2476325.28612979644879.6052371822476510.31193963 644779.97595496
2476570.08950896644697.4259782622476819.16271451644627.685480707
#Sta/Elev= 30
       0 2109.27    35.3 2088.96    47.1 2081.04    56.2 2077.14    69.5 2068.79
   124.3 2038.04   134.5 2034.22   151.6  2025.3   161.8 2020.84   169.7 2018.12
   181.7 2016.02   217.7 2016.56   224.5 2016.14  241.662009.644   245.6 2008.64
     251  2008.3  268.662009.645   285.9 2011.56   299.5 2016.47   305.3 2016.98
   337.4 2015.96   375.1 2016.36   391.7 2015.64   395.8 2016.25   408.3  2019.6
   449.8 2025.04   462.3  2028.9   487.2 2039.02   532.1 2053.46   570.7 2069.91
#Mann= 3 ,-1 , 0
       0      .1       0  241.66    .045       0  268.66      .1       0
Bank Sta=241.66,268.66
XS Rating Curve= 0 ,0
Exp/Cntr(USF)=0,0
Exp/Cntr=0.3,0.1

Type RM Length L Ch R = 1 ,6536    ,204.8,202.3,199.8
XS GIS Cut Line= 4
 2476410.6826574644972.1181421022476545.89382613644899.531093626
2476668.29551572644856.8328298172476843.35839734644747.240619373
#Sta/Elev= 30
       0 2064.27    11.1 2058.98    36.4 2045.21    45.3 2041.85      50 2039.23
    74.8 2027.92    81.8    2025    95.4 2020.51   113.6    2017   145.7 2014.28
   158.6 2012.58   179.8  2007.1   196.7 2006.08  212.822000.589   217.9 1999.13
   222.1 1999.09  230.192000.587   243.3 2002.33   247.6 2003.75     256 2007.63
   264.5 2007.96   277.2 2006.35   300.1 2010.96   347.8 2015.15   370.5 2018.56
   384.8 2023.61   394.5 2025.19     404 2029.23   440.1 2041.54   489.6 2062.35
#Mann= 3 ,-1 , 0
       0      .1       0  212.82    .045       0  230.19      .1       0
Bank Sta=212.82,230.19
XS Rating Curve= 0 ,0
Exp/Cntr(USF)=0,0
Exp/Cntr=0.3,0.1

Type RM Length L Ch R = 1 ,6333    ,353.1,357.1,359.1
XS GIS Cut Line= 4
2476538.77744883645161.4137783232476648.36965928645091.673280768
2476749.42221696645017.662956832 2476934.4480268644905.224195467
#Sta/Elev= 30
       0 2050.77    12.1 2043.72    45.3 2026.36    62.6 2018.42    77.1 2013.06
   118.5 2003.26   132.8 1998.16   137.8 1996.98   155.1 1997.13   172.5 1998.89
   178.6 1997.72  188.071992.256   192.3 1991.21     198 1990.86  206.991992.255
   223.7 1997.57   246.3 2002.13   266.1 2002.06   283.6 2002.89   306.7 2005.38
   313.5 2006.57   322.2 2009.11   364.4 2019.07   374.6  2022.4   386.2 2028.39
   397.9 2030.76   406.8 2036.27   424.1 2044.13   448.6 2056.26   471.7 2065.35
#Mann= 3 ,-1 , 0
       0      .1       0  188.07    .045       0  206.99      .1       0
Bank Sta=188.07,206.99
XS Rating Curve= 0 ,0
Exp/Cntr(USF)=0,0
Exp/Cntr=0.3,0.1

Type RM Length L Ch R = 1 ,5976    ,206.4,203.9,200.7
XS GIS Cut Line= 4
2476601.40156909645397.6775047342476693.91447401645363.518893687
2476814.89288813645323.6671807982477079.62212375 645194.14911391
#Sta/Elev= 30
       0 2085.46    14.2 2075.63    35.5 2061.62    84.2 2032.77    99.5 2023.05
   103.7 2019.61   125.1 1999.88   131.5 1993.18   141.6 1981.25  145.451978.343
   150.5 1976.83   154.2 1976.86   158.5 1977.58  160.351978.343   166.9 1980.89
   191.6 1983.27   226.5 1983.88   248.1 1986.67   252.5 1986.49   261.5 1984.97
   265.9 1984.89   288.2 1989.55   319.2 1992.59   349.1 1996.66   363.9 1999.17
   386.1 2003.84   430.7 2017.94   475.2 2029.09   504.5 2038.69   520.7  2044.5
#Mann= 3 ,-1 , 0
       0      .1       0  145.45    .045       0  160.35      .1       0
Bank Sta=145.45,160.35
XS Rating Curve= 0 ,0
Exp/Cntr(USF)=0,0
Exp/Cntr=0.3,0.1

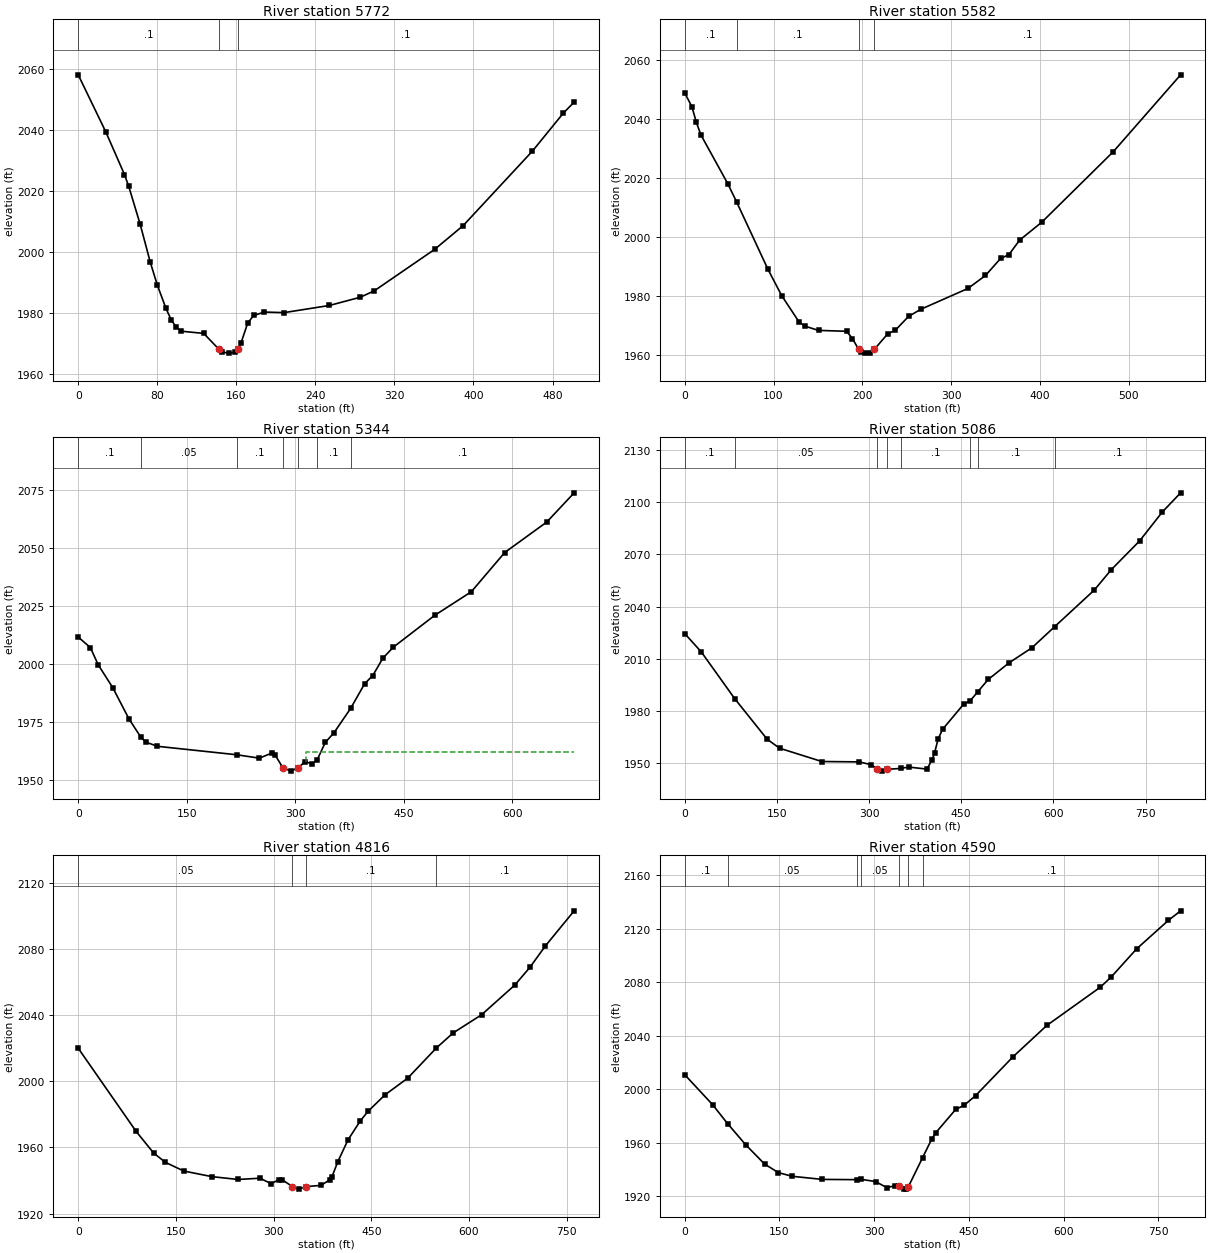
Type RM Length L Ch R = 1 ,5772    ,190,190.1,189.5
XS GIS Cut Line= 4
2476735.18946236645589.8196918762476816.31616359645538.581775305
2476958.64370962 645421.873187562477146.51607038645303.741324354
#Sta/Elev= 30
       0 2058.15    27.9 2039.42    46.8 2025.41    51.1 2021.55    62.7 2009.07
    72.9 1996.63    79.9 1989.25    88.8 1981.43    94.1 1977.69    99.1 1975.29
   104.3 1973.94     127 1973.22  142.531967.961   145.9 1967.08   152.2 1966.74
   158.5 1966.97  161.31 1967.96   164.9 1970.23   171.5 1976.59   177.5  1979.1
   188.4 1980.23   208.3 1980.04   254.3  1982.4   285.6 1985.11   299.7 1987.22
   360.6 2000.79   389.6 2008.63   459.7 2033.11   491.1 2045.63   501.9 2049.19
#Mann= 3 ,-1 , 0
       0      .1       0  142.53    .045       0  161.31      .1       0
Bank Sta=142.53,161.31
XS Rating Curve= 0 ,0
Exp/Cntr(USF)=0,0
Exp/Cntr=0.3,0.1

Type RM Length L Ch R = 1 ,5582    ,238.8,237.9,236.5
XS GIS Cut Line= 4
2476816.31616359645777.6920526372476907.40579305645707.951555082
2477089.58505197645552.8145299082477251.83845445645428.989564861
#Sta/Elev= 30
       0 2048.71     8.1 2044.05    13.1 2038.78    18.2 2034.49    48.4 2017.98
   58.492011.716    93.7 1988.89   109.3  1979.9   128.7 1971.05   134.9 1969.66
   150.6 1968.18   182.2 1967.87   188.8 1965.41  195.681961.769   197.9 1960.86
     203 1960.47   208.4 1960.66  213.481961.771   228.5 1967.02     237 1968.22
   252.1 1972.96   266.2  1975.4   318.8  1982.4   338.5  1986.8   355.5 1992.56
   364.8 1993.84     377  1998.8   401.9 2004.87   482.4 2028.79   558.1 2054.83
#Mann= 4 ,-1 , 0
       0      .1       0   58.49      .1       0  195.68    .045       0
  213.48      .1       0
Bank Sta=195.68,213.48
XS Rating Curve= 0 ,0
Exp/Cntr(USF)=0,0
Exp/Cntr=0.3,0.1

Type RM Length L Ch R = 1 ,5344    ,256.8,258.4,259.2
XS GIS Cut Line= 4
 2476934.4480268646013.9557790482477108.08763296645853.125652033
2477207.71691518 645743.533441592477394.16600048645507.269715178
#Sta/Elev= 30
       0 2011.44    16.8 2006.91    27.7 1999.45    47.7 1989.65    70.3 1976.08
    86.51968.326    93.1  1966.2   109.4 1964.33  219.521960.669   250.5 1959.21
   268.5 1961.51   272.1 1960.67  283.041955.049   294.1 1953.62  303.851955.048
   313.8 1957.66   323.9 1956.79  330.671958.615   341.7 1966.01   353.6 1970.13
  376.731980.674   396.1 1991.32   407.3 1994.83   421.3 2002.33   435.8 2007.09
     493  2020.8   543.6 2030.98   589.8  2047.9     648 2061.06   685.8 2073.64
#Mann= 7 ,-1 , 0
       0      .1       0    86.5     .05       0  219.52      .1       0
  283.04    .045       0  303.85      .1       0  330.67      .1       0
  376.73      .1       0
#XS Ineff= 2 , 0
       0                   315.4       0    1962
Permanent Ineff=
       F       F
Bank Sta=283.04,303.85
XS Rating Curve= 0 ,0
Exp/Cntr(USF)=0,0
Exp/Cntr=0.3,0.1

Type RM Length L Ch R = 1 ,5086    ,265.7,269.3,271.2
XS GIS Cut Line= 4
 2477024.1143808 646206.097966192477243.29880169646062.347144699
2477374.24014403645934.2523532712477586.30818762645641.057608447
#Sta/Elev= 30
       0  2024.6    27.1 2014.01   81.491987.168   134.2 1963.92   154.4 1958.76
   223.2 1951.12     284  1950.9   303.8 1949.27   312.8 1946.76   320.7  1945.6
   328.5 1946.63  351.251947.138   364.3 1947.94   394.3 1946.76   402.8 1952.21
   406.8 1956.21   412.4    1964   419.7 1969.59   453.8 1983.96  464.83 1986.06
  476.971991.158   493.9  1998.2   528.4  2007.9   565.1 2016.41  602.062028.512
   666.7 2049.57   694.4  2061.3   740.3 2077.73   777.5 2094.42   807.1 2105.36
#Mann= 8 ,-1 , 0
       0      .1       0   81.49     .05       0   312.8    .045       0
   328.5     .05       0  351.25      .1       0  464.83      .1       0
  476.97      .1       0  602.06      .1       0
Bank Sta=312.8,328.5
XS Rating Curve= 0 ,0
Exp/Cntr(USF)=0,0
Exp/Cntr=0.3,0.1

Type RM Length L Ch R = 1 ,4816    ,226.4,226.9,225.5
XS GIS Cut Line= 4
2477123.74366302646328.499655777  2477321.578952646226.023822635
2477519.41424099646156.2833250792477821.14863857646025.341982731
#Sta/Elev= 30
       0 2019.96      89 1969.67     116 1956.55     134    1951   162.1 1945.77
   205.2 1942.39   245.2 1940.68   279.2 1941.43   296.1 1938.15   307.7 1940.45
   313.1 1940.49     3291936.375   338.6 1934.84  350.041936.375   372.5  1937.1
   386.1 1940.37   389.4 1942.07   398.6  1951.4   414.3 1964.62   433.1 1976.04
   444.9 1981.78   471.1  1991.8     506  2001.9  549.462019.914   575.7  2029.2
   619.3 2040.15   670.3 2058.08   693.5 2068.77   717.4 2081.78   761.5 2102.95
#Mann= 4 ,-1 , 0
       0     .05       0     329    .045       0  350.04      .1       0
  549.46      .1       0
#XS Ineff= 2 , 0
          309.85  1940.3
Permanent Ineff=
       F       F
Bank Sta=329,350.04
XS Rating Curve= 0 ,0
Exp/Cntr(USF)=0,0
Exp/Cntr=0.3,0.1

Type RM Length L Ch R = 1 ,4590    ,214.4,220.7,223.9
XS GIS Cut Line= 4
2477221.94966978646507.8323637762477448.25046797646412.472907935
2477631.85300235646321.3832784752477933.58739994646176.209181524
#Sta/Elev= 30
       0 2010.77    44.3 1988.27   67.841974.212    96.4 1958.44   126.5 1943.93
   148.4  1937.5   170.1 1934.77   217.9 1932.43  272.691932.234  279.091932.511
   302.3 1930.82   319.8 1926.36   333.2 1927.63   339.1  1927.2   348.1 1925.16
   351.1 1925.23  354.261926.965  376.641948.589   391.2 1962.54   397.8 1967.41
   429.1 1984.72   442.6 1987.88   460.6 1995.02   519.8 2024.05   573.6 2047.59
   658.4 2076.22   675.7 2083.91   715.6 2104.77   766.2 2126.22   785.4 2133.27
#Mann= 7 ,-1 , 0
       0      .1       0   67.84     .05       0  272.69      .1       0
  279.09     .05       0   339.1    .045       0  354.26     .05       0
  376.64      .1       0
Bank Sta=339.1,354.26
XS Rating Curve= 0 ,0
Exp/Cntr(USF)=0,0
Exp/Cntr=0.3,0.1

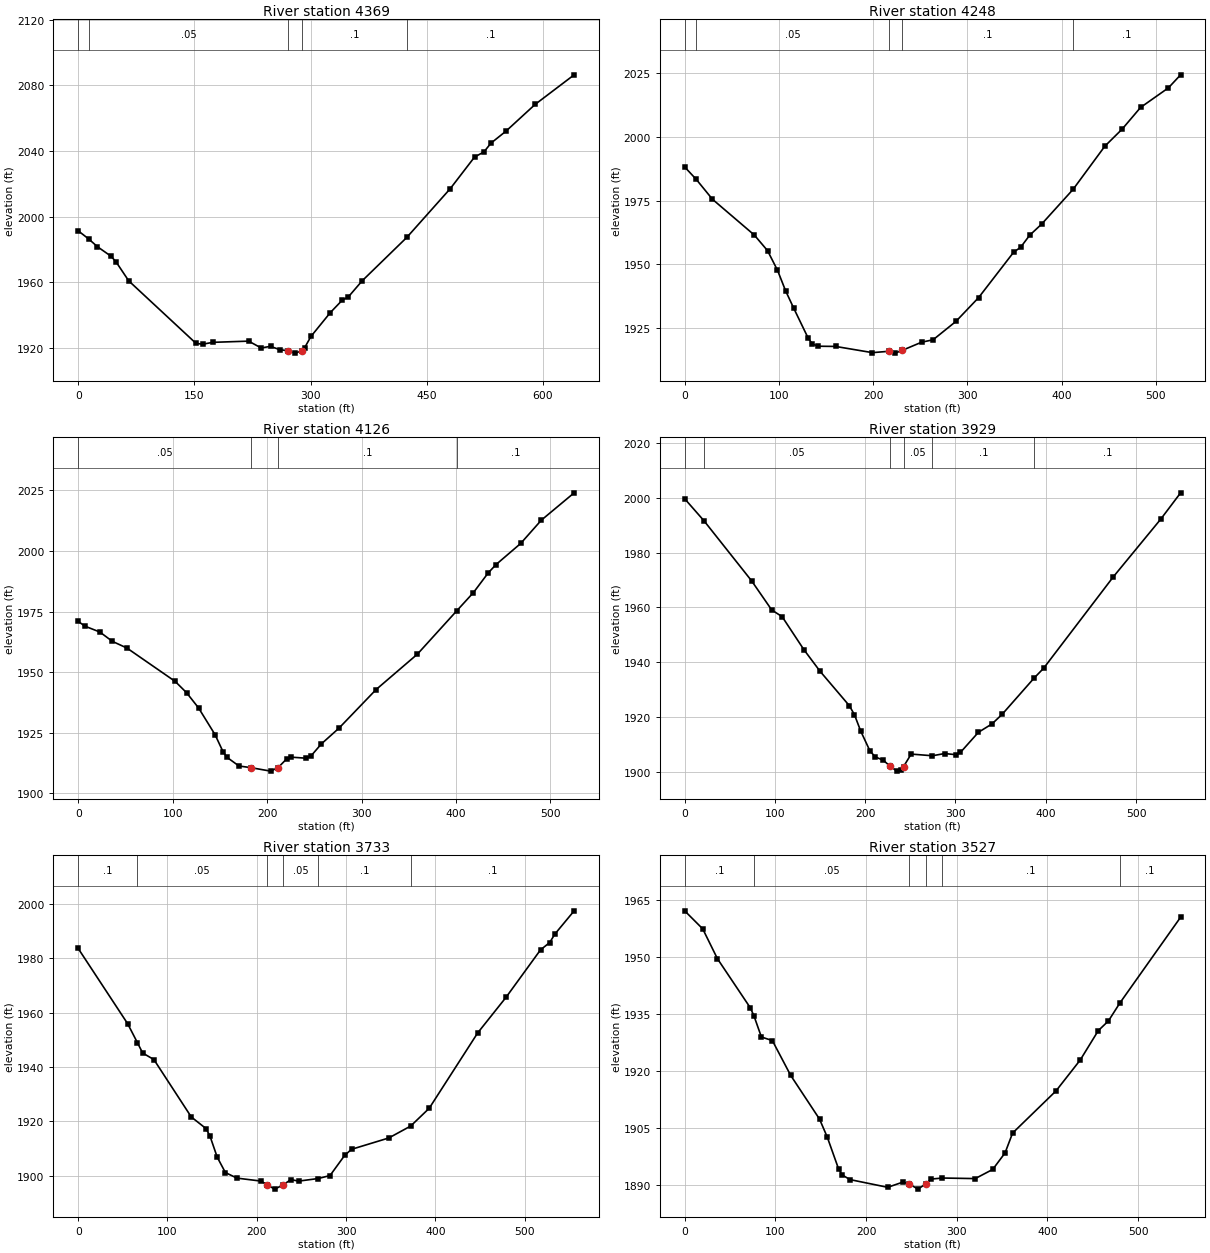
Type RM Length L Ch R = 1 ,4369    ,121.6,120.8,120.7
XS GIS Cut Line= 4
2477298.80654464646651.5831852672477482.40907902 646573.30303495
2477630.42972689646590.3823404742477896.58223797646470.827201808
#Sta/Elev= 30
       0 1991.29   13.461986.343    24.9 1981.57    42.6 1975.71    49.3 1972.03
    65.2 1960.77   152.1 1922.59   160.8 1922.09   173.9 1923.23   220.1 1923.96
   236.2  1919.8   248.3 1920.78   260.3 1918.73  271.021918.127   280.5 1916.64
  289.271918.127   292.5 1920.05   300.6 1926.87   325.6 1941.41   340.9 1948.93
   348.9    1951   366.6 1960.74  424.351987.284   480.5 2017.07   511.8 2036.32
   523.9 2039.45     533 2044.81   552.4 2052.13   590.1 2068.48   640.4  2086.5
#Mann= 5 ,-1 , 0
       0      .1       0   13.46     .05       0  271.02    .045       0
  289.27      .1       0  424.35      .1       0
#XS Ineff= 2 , 0
           248.6 1920.67
Permanent Ineff=
       F       F
Bank Sta=271.02,289.27
XS Rating Curve= 0 ,0
Exp/Cntr(USF)=0,0
Exp/Cntr=0.3,0.1

Type RM Length L Ch R = 1 ,4248    ,129.4,121.6,118.1
XS GIS Cut Line= 4
2477319.31031149646751.5181849532477468.91444764646691.676530496
2477636.22682847646710.6060334372477823.07934136646648.932491598
#Sta/Elev= 30
       0 1988.25    12.3 1983.38    29.5 1975.57    73.9 1961.53    87.9 1955.42
    98.5 1947.71   107.1 1939.63   115.7 1932.82   130.9 1921.17   135.4 1918.76
   141.6 1917.87   160.1 1917.79   199.2 1915.35   216.3 1915.87   223.4 1915.16
   230.8 1916.24   251.5 1919.46   263.6 1920.39   287.8  1927.6   311.9 1936.95
     349 1954.74   356.6 1956.76   366.1 1961.44   378.8 1965.82   412.2 1979.47
   445.9 1996.42   464.3 2003.14   483.8 2011.63   513.3 2019.31   526.3 2024.44
#Mann= 5 ,-1 , 0
       0      .1       0    12.3     .05       0   216.3    .045       0
   230.8      .1       0   412.2      .1       0
Bank Sta=216.3,230.8
XS Rating Curve= 0 ,0
Exp/Cntr(USF)=0,0
Exp/Cntr=0.3,0.1

Type RM Length L Ch R = 1 ,4126    ,201.5,197.8,195.1
XS GIS Cut Line= 4
2477352.89101213646877.8839834562477459.63667165646843.725372409
 2477604.8107686646795.3340067582477842.49777048646690.011622696
#Sta/Elev= 30
       0 1970.99       7 1969.02    22.9 1966.59    36.1 1962.75    51.6 1959.97
   102.7  1946.2   114.7 1941.56   127.4 1935.29   144.9 1924.23   153.3 1917.25
   157.5  1914.9   170.2 1911.32  182.891910.629   203.7  1909.2  211.541910.629
   220.8 1914.28     225 1914.98   241.7 1914.52   246.1  1915.3   257.5 1920.45
     276 1926.89   315.4 1942.85   359.1 1957.45  400.811975.344   418.5 1982.88
     434 1990.92   442.2 1994.35   468.5 2003.13   490.4 2012.75   525.1 2024.01
#Mann= 4 ,-1 , 0
       0     .05       0  182.89    .045       0  211.54      .1       0
  400.81      .1       0
Bank Sta=182.89,211.54
XS Rating Curve= 0 ,0
Exp/Cntr(USF)=0,0
Exp/Cntr=0.3,0.1

Type RM Length L Ch R = 1 ,3929    ,193.3,195.4,197.8
XS GIS Cut Line= 4
2477428.32461153647102.7615061852477563.53578026647035.867559551
2477721.51935635646916.3124208852477893.73568705646813.836587743
#Sta/Elev= 30
       0 1999.63   21.351991.615    74.1  1969.7    96.4 1959.07     108 1956.59
   132.1 1944.55     150 1936.67   182.4 1924.12   188.1 1920.81     195 1914.86
   205.2 1907.64     211 1905.47   220.1 1904.19  227.971901.929   235.1 1900.24
   239.5 1900.54  242.531901.927   250.9 1906.46   274.5 1905.85     288 1906.66
   300.4 1906.24   305.4 1907.04   325.4 1914.41   340.5 1917.48   351.8 1921.01
  387.06 1934.19   397.6 1937.77   474.8 1971.13   527.3 1992.16   549.4  2001.8
#Mann= 6 ,-1 , 0
       0      .1       0   21.35     .05       0  227.97    .045       0
  242.53     .05       0   274.5      .1       0  387.06      .1       0
#XS Ineff= 2 , 0
                          251.51         1906.36
Permanent Ineff=
       F       F
Bank Sta=227.97,242.53
XS Rating Curve= 0 ,0
Exp/Cntr(USF)=0,0
Exp/Cntr=0.3,0.1

Type RM Length L Ch R = 1 ,3733    ,204.9,205.8,206.6
XS GIS Cut Line= 4
2477537.91682197647213.7769920892477681.66764346 647168.23217736
2477832.53484225647107.031332566 2478046.0261613646993.169295741
#Sta/Elev= 30
       0 1983.67    55.4 1955.97   66.341948.985    72.2 1945.19    84.8 1942.77
   126.7 1921.63   143.2 1917.36   147.7 1914.52   155.7 1906.85   164.9 1901.16
   177.9 1899.12   204.9 1898.03  211.621896.626   220.2 1895.07  229.471896.626
   238.3 1898.58   246.9 1898.02  268.841898.969   282.1 1900.07   298.7 1907.58
   306.2 1909.73   347.9  1913.9  372.44 1918.29   393.2 1924.83   447.6 1952.62
   479.3  1965.7   517.9 1983.16   528.2 1985.87   534.1 1989.02   555.6 1997.54
#Mann= 6 ,-1 , 0
       0      .1       0   66.34     .05       0  211.62    .045       0
  229.47     .05       0  268.84      .1       0  372.44      .1       0
Bank Sta=211.62,229.47
XS Rating Curve= 0 ,0
Exp/Cntr(USF)=0,0
Exp/Cntr=0.3,0.1

Type RM Length L Ch R = 1 ,3527    ,189.7,195.6,194.3
XS GIS Cut Line= 4
2477554.99612749647387.4165982472477714.40297905647364.644190882
2477920.77792079647303.4433460892478074.49167051647229.433022153
#Sta/Elev= 30
       0 1962.21    19.9 1957.45    36.1 1949.58    72.5 1936.58   76.581934.366
    84.6 1928.92    96.7 1927.97   116.9 1918.79   148.7 1907.26   157.3 1902.47
   169.7 1894.12   173.9  1892.5   182.2  1891.3   223.9 1889.26   240.7 1890.64
   247.9 1890.11   257.3 1888.78  266.111890.217   272.1 1891.44  284.24 1891.71
   320.4 1891.56   339.7 1893.98   353.3 1898.34   361.6 1903.57   409.5  1914.7
   436.2 1922.85   456.1  1930.6   467.3 1933.16  479.871937.874   546.9 1960.53
#Mann= 6 ,-1 , 0
       0      .1       0   76.58     .05       0   247.9    .045       0
  266.11     .05       0  284.24      .1       0  479.87      .1       0
#XS Ineff= 2 , 0
                          285.28         1891.47
Permanent Ineff=
       F       F
Bank Sta=247.9,266.11
XS Rating Curve= 0 ,0
Exp/Cntr(USF)=0,0
Exp/Cntr=0.3,0.1

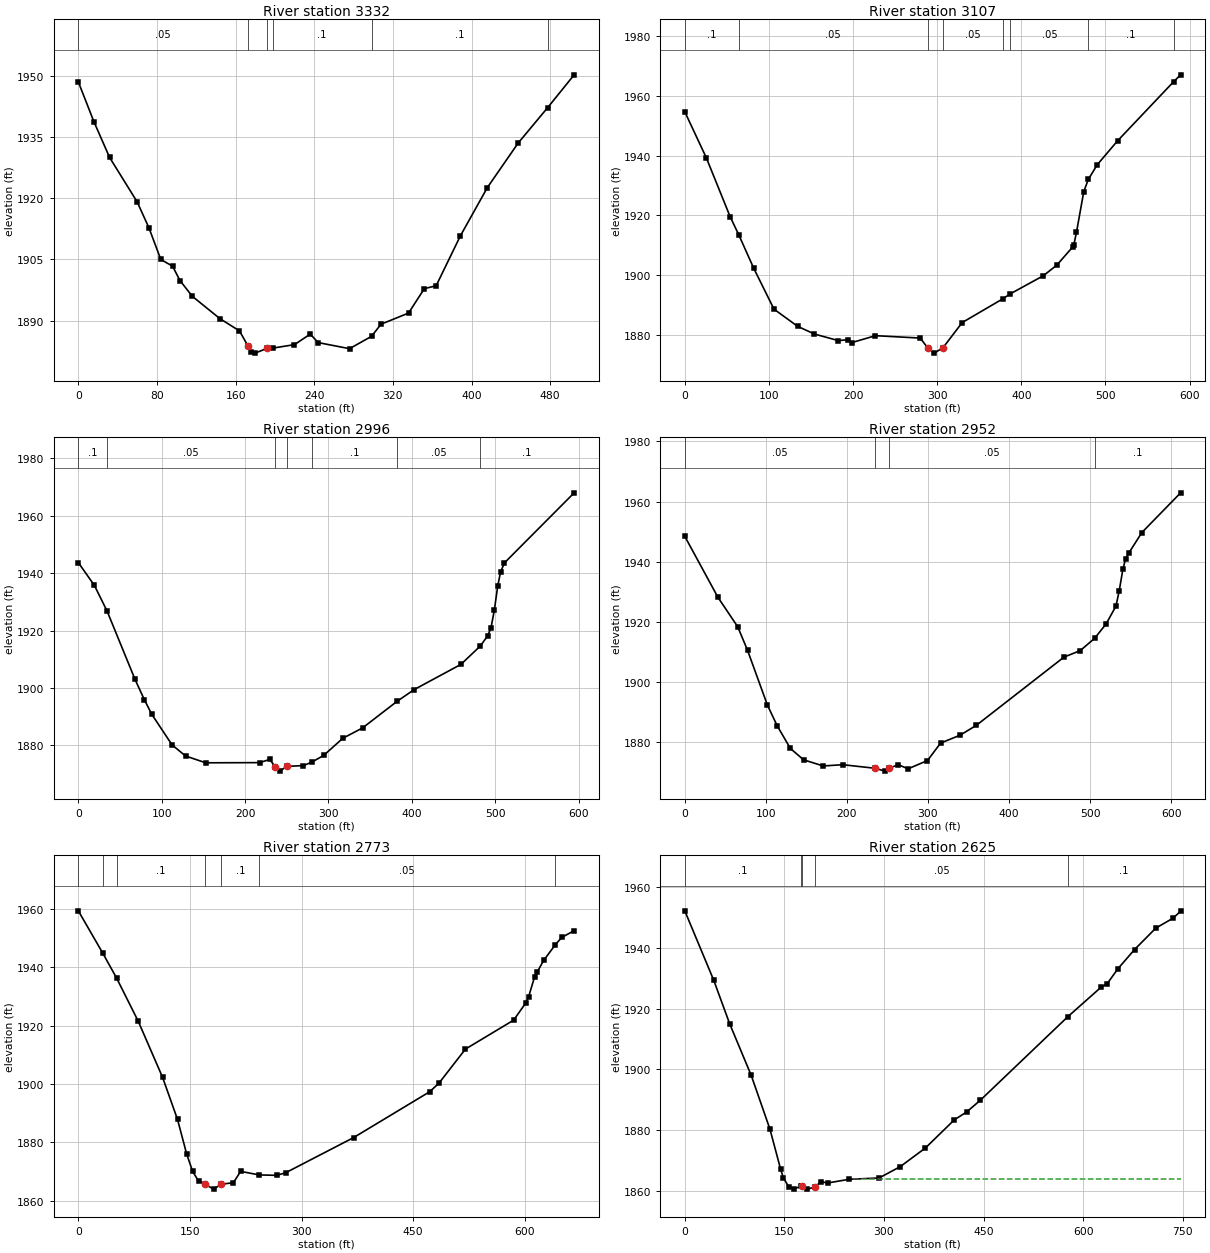
Type RM Length L Ch R = 1 ,3332    ,221.3,225.3,223.9
XS GIS Cut Line= 4
2477554.99612749647501.2786350722477697.32367352647508.395012373
2477898.00551343647505.5484614532478058.83564044 647494.16225777
#Sta/Elev= 30
       0 1948.48    15.8 1938.76    31.8 1929.97    59.8 1919.11    71.8 1912.74
    83.9 1904.98    95.9 1903.33   103.4 1899.82   115.9 1895.97   143.9 1890.51
   163.9 1887.49  172.691883.744   175.9 1882.33   179.9 1882.04   191.9 1883.21
  197.851883.271   219.9 1884.12   235.9  1886.7     244 1884.62   275.9 1883.13
  298.241886.153   307.9 1889.12   335.9 1891.85     352 1897.84     364 1898.54
   388.6 1910.74   416.1  1922.6   447.5 1933.52  477.371942.155   504.4 1950.21
#Mann= 6 ,-1 , 0
       0     .05       0  172.69    .045       0   191.9     .05       0
  197.85      .1       0  298.24      .1       0  477.37      .1       0
#XS Ineff= 2 , 0
                          235.69         1886.65
Permanent Ineff=
       F       F
Bank Sta=172.69,191.9
XS Rating Curve= 0 ,0
Exp/Cntr(USF)=0,0
Exp/Cntr=0.3,0.1

Type RM Length L Ch R = 1 ,3107    ,110.5,110.7,110.2
XS GIS Cut Line= 4
2477513.21686523  647659.88426882477742.30647108647682.054230656
2477887.41894868  647714.30144792478097.69767779647723.706886263
#Sta/Elev= 30
       0 1954.68    25.6 1939.24    53.8 1919.57   64.211913.388    81.9 1902.24
     106 1888.51   134.2 1882.73   154.1 1880.17   182.4 1877.97   194.4 1878.27
   198.5  1877.3   226.6 1879.62   279.8 1878.82  288.811875.499   296.2 1873.77
  306.66  1875.5   329.7 1884.02  378.131892.005  386.861893.648   426.2 1899.73
   442.2 1903.29   461.3 1909.45   462.2 1909.86   465.5 1914.24   474.2 1927.94
  479.621932.027   490.2 1936.93   514.3 1944.93  581.061964.791   589.3 1967.07
#Mann= 8 ,-1 , 0
       0      .1       0   64.21     .05       0  288.81    .045       0
  306.66     .05       0  378.13      .1       0  386.86     .05       0
  479.62      .1       0  581.06     .12       0
#XS Ineff= 2 , 0
          225.21 1879.47
Permanent Ineff=
       F       F
Bank Sta=288.81,306.66
XS Rating Curve= 0 ,0
Exp/Cntr(USF)=0,0
Exp/Cntr=0.5,0.3

Type RM Length L Ch R = 1 ,2996    ,45.9,44.2,44.2
XS GIS Cut Line= 4
2477523.68406737647761.7380443092477641.81593057647780.240625293
2477861.00035146647811.552685419 2478114.3433834647797.319930816
#Sta/Elev= 30
       0 1943.68    19.3 1935.72   34.581926.726    67.9 1903.05    79.1 1895.96
    88.1 1890.82   112.4 1880.17   128.6  1876.3   152.8 1873.92   217.5 1873.98
   229.6  1875.1   235.9 1872.62   241.7 1871.02     250 1872.67     270 1872.96
   279.91874.132   294.3  1876.5   317.2 1882.46     341 1886.09  382.221895.326
   402.8 1899.43   458.9 1908.22  482.08  1914.6     491 1918.17     495 1921.05
     499 1927.17     503 1935.52   506.4 1940.36     511 1943.57   594.7    1968
#Mann= 7 ,-1 , 0
       0      .1       0   34.58     .05       0   235.9    .045       0
     250     .05       0   279.9      .1       0  382.22     .05       0
  482.08      .1       0
#XS Ineff= 2 , 0
             215 1872.04     270         1872.04
Permanent Ineff=
       F       F
Bank Sta=235.9,250
XS Rating Curve= 0 ,0
Exp/Cntr(USF)=0,0
Exp/Cntr=0.5,0.3

Type RM Length L Ch R = 1 ,2952    ,176.4,178.4,175.2
XS GIS Cut Line= 4
2477506.49869497647800.9658442462477702.66926655647835.900329594
2477879.35714437647848.6648530872478114.49310344647841.274865802
#Sta/Elev= 30
       0 1948.39    40.9 1928.07    65.3 1918.26    77.4 1910.43   101.8 1892.25
     114 1885.26   130.3 1877.71   146.5 1873.95   170.7 1871.89     195 1872.31
     235 1871.11     247 1870.17   251.5 1871.12   263.5  1872.3   275.5 1870.94
   299.4  1873.7   315.6 1879.52   339.7 1882.15   359.7 1885.43   467.8 1908.16
   487.8 1910.31  505.63 1914.42   519.9 1919.27   531.9 1925.14   535.9 1930.19
   540.5 1937.47   543.9 1940.97   547.9 1942.88   563.9 1949.67   611.7 1962.89
#Mann= 4 ,-1 , 0
       0     .05       0     235    .045       0   251.5     .05       0
  505.63      .1       0
Bank Sta=235,251.5
XS Rating Curve= 0 ,0
Exp/Cntr(USF)=0,0
Exp/Cntr=0.5,0.3

Type RM Length L Ch R = 1 ,2773    ,148.9,148.7,147.5
XS GIS Cut Line= 4
2477492.37200724647955.303506911 2477597.6943913647979.499189736
 2477748.5615901 647999.425046182478151.34854536647948.187129609
#Sta/Elev= 30
       0 1959.23   33.071944.649    51.61936.146    80.4 1921.52   113.2 1902.29
   133.3 1887.87   145.4 1876.23   153.5 1870.16   161.6 1866.76  169.961865.767
   181.8 1864.05   192.31865.769   208.3 1866.22   218.1 1870.12  242.951868.915
   266.5 1868.76   278.6 1869.65     370 1881.69   472.1 1897.35   484.5 1900.25
   520.2 1911.94     585 1921.85   601.2 1927.69   605.2 1929.92   613.2 1936.72
   616.8 1938.38   625.3 1942.27  641.161947.684   649.5 1950.11   666.3 1952.45
#Mann= 7 ,-1 , 0
       0      .1       0   33.07     .05       0    51.6      .1       0
  169.96    .045       0   192.3      .1       0  242.95     .05       0
  641.16     .12       0
Bank Sta=169.96,192.3
XS Rating Curve= 0 ,0
Exp/Cntr(USF)=0,0
Exp/Cntr=0.3,0.1

Type RM Length L Ch R = 1 ,2625    ,248.2,247.9,244.4
XS GIS Cut Line= 4
 2477479.5625281648113.2870830052477606.23404407648130.366388529
2477789.83657845648141.7525922112478209.70283924648027.890555387
#Sta/Elev= 30
       0 1952.22    43.6 1929.34    67.8  1914.9   100.1    1898   128.3 1880.27
   144.4 1867.05   148.4 1864.37   156.4 1861.34   164.4 1860.65  174.541861.445
   176.4 1861.49   184.4 1860.56   196.7 1861.29   204.5    1863   215.6  1862.6
   247.4 1863.79   292.6 1864.23   324.6 1867.98   362.4 1874.11   406.1 1883.41
   424.6 1885.98   445.3 1889.87  576.621917.292   627.4 1927.14     636 1928.16
   652.6 1933.21   677.4 1939.46   709.3  1946.5   735.5 1949.82   746.8  1952.1
#Mann= 5 ,-1 , 0
       0      .1       0  174.54     .05       0   176.4    .045       0
   196.7     .05       0  576.62      .1       0
#XS Ineff= 2 , 0
                          253.06         1863.92
Permanent Ineff=
       F       F
Bank Sta=176.4,196.7
XS Rating Curve= 0 ,0
Exp/Cntr(USF)=0,0
Exp/Cntr=0.3,0.1

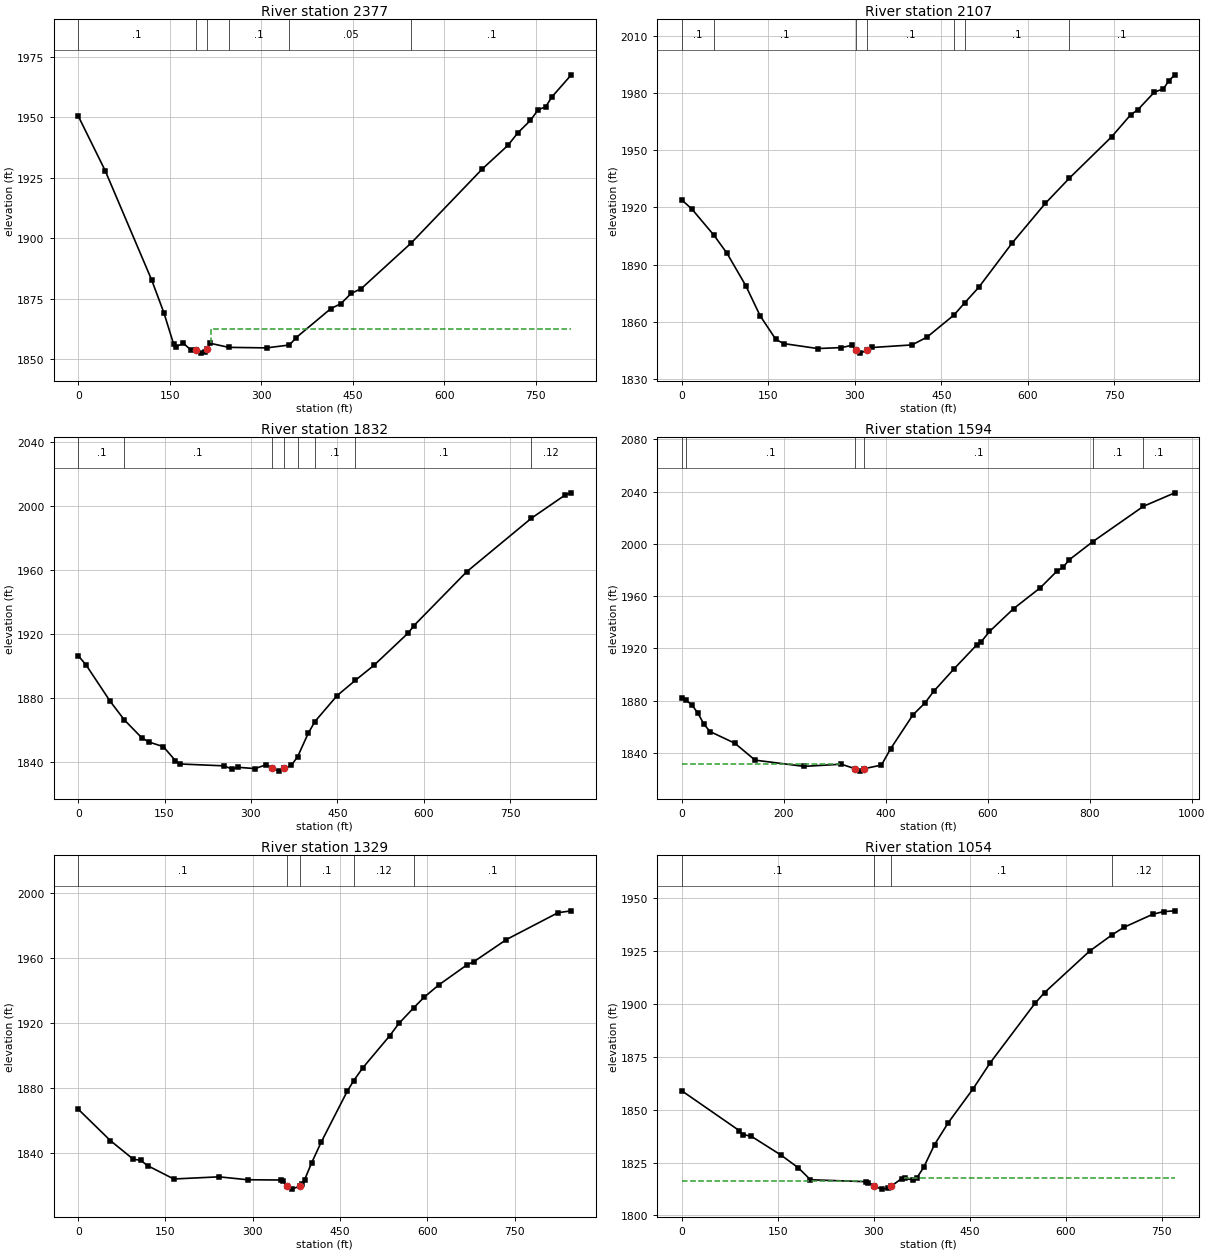
Type RM Length L Ch R = 1 ,2377    ,272.4,269.4,265.1
XS GIS Cut Line= 4
2477442.55736613648370.8999413212477579.19181032 648363.78356402
2477821.14863857648343.8577075752478235.32179752648232.842221671
#Sta/Elev= 30
       0 1950.55    44.2 1927.96   120.4 1882.78   140.4 1869.26   156.4 1856.28
   160.5 1855.21   172.5 1856.55   184.5 1853.88   192.9 1853.98   200.6 1852.51
   207.7    1853  210.55 1854.13   216.6 1856.57  246.781854.892     309 1854.68
   346.41855.883   357.1 1858.87   414.3 1870.93   430.7 1872.95   447.5  1877.2
   464.1 1879.18  545.981898.042   662.5 1928.65   704.3 1938.34   720.8 1943.58
   741.5 1948.74   754.1 1953.13   766.4 1954.33   776.5 1958.39   808.4 1967.55
#Mann= 6 ,-1 , 0
       0      .1       0   192.9    .045       0  210.55      .1       0
  246.78      .1       0   346.4     .05       0  545.98      .1       0
#XS Ineff= 2 , 0
                          217.96         1862.54
Permanent Ineff=
       F       F
Bank Sta=192.9,210.55
XS Rating Curve= 0 ,0
Exp/Cntr(USF)=0,0
Exp/Cntr=0.3,0.1

Type RM Length L Ch R = 1 ,2107    ,272.7,275.4,276.6
XS GIS Cut Line= 4
2477485.25562994648691.1369198912477614.77369683648668.364512526
2477933.58739994648497.5714572892478285.13643863 648413.59820513
#Sta/Elev= 30
       0 1924.03    17.8 1919.14   56.111905.351    78.7 1895.85   111.2 1878.84
     136 1863.06   163.2 1850.63   176.9 1848.44   235.8 1845.84   276.7 1846.34
   294.8 1847.53  302.321845.015   309.9 1843.43  321.141845.017   330.5 1846.39
   399.2 1847.75   425.1 1851.82  471.86 1863.44  490.761869.947   514.9 1878.03
   572.7  1901.3   630.1 1922.11  672.131935.472   745.1 1957.14   778.1 1968.71
   790.5 1971.35   819.3 1980.66     835 1982.36   843.9 1986.48   854.6 1989.74
#Mann= 7 ,-1 , 0
       0      .1       0   56.11      .1       0  302.32    .045       0
  321.14      .1       0  471.86     .12       0  490.76      .1       0
  672.13      .1       0
Bank Sta=302.32,321.14
XS Rating Curve= 0 ,0
Exp/Cntr(USF)=0,0
Exp/Cntr=0.3,0.1

Type RM Length L Ch R = 1 ,1832    ,236.9,238.1,238.6
XS GIS Cut Line= 4
 2477597.6943913648908.898065318 2477755.6779674648859.083424207
 2478060.2589159648763.723968366 2478404.6915773648624.242973256
#Sta/Elev= 30
       0 1906.61    13.7  1900.8    55.6 1878.12   80.111866.534   110.1 1855.49
   122.7 1852.76   147.9 1849.84   168.9  1841.1   177.2 1839.03   252.7 1837.88
   267.2 1835.91   277.8 1836.95   307.2 1836.17   326.9 1838.61   336.5 1836.24
   349.1 1834.58  356.681836.232   370.1 1838.17  381.141843.598   399.4 1858.12
  411.071865.497   449.7 1881.71  481.481891.277   513.4 1900.51   573.4 1920.84
   582.9 1925.29   674.7 1958.95  787.011992.329   845.7 2006.84   856.4  2008.2
#Mann= 8 ,-1 , 0
       0      .1       0   80.11      .1       0   336.5    .045       0
  356.68      .1       0  381.14      .1       0  411.07      .1       0
  481.48      .1       0  787.01     .12       0
Bank Sta=336.5,356.68
XS Rating Curve= 0 ,0
Exp/Cntr(USF)=0,0
Exp/Cntr=0.3,0.1

Type RM Length L Ch R = 1 ,1594    ,260.7,264.7,268.8
XS GIS Cut Line= 4
2477594.84784038649066.8816414122477875.23310606 649056.91871319
2478050.29598768 649011.373898462478552.71222517648955.866155508
#Sta/Elev= 30
       0 1882.44    8.121880.463    19.9  1876.9    31.9 1870.46    43.9 1861.85
    55.9 1856.37   104.3 1847.47     144 1834.54     240 1829.78   313.1 1831.44
  340.351827.938   350.3 1826.14  357.121827.939   391.7 1830.78   409.7 1843.26
   453.7 1869.31   476.8 1878.16   494.1 1887.18   534.3  1904.5   578.6 1922.74
   586.7 1924.82   603.6    1933     651 1950.52   703.4 1966.52   735.6 1979.09
   747.6    1982   759.7 1987.79  806.012001.699  905.45  2028.8   966.9 2039.11
#Mann= 6 ,-1 , 0
       0      .1       0    8.12      .1       0  340.35    .045       0
  357.12      .1       0  806.01      .1       0  905.45      .1       0
#XS Ineff= 2 , 0
          311.35 1831.69
Permanent Ineff=
       F       F
Bank Sta=340.35,357.12
XS Rating Curve= 0 ,0
Exp/Cntr(USF)=0,0
Exp/Cntr=0.3,0.1

Type RM Length L Ch R = 1 ,1329    ,273.6,275.2,277
XS GIS Cut Line= 4
2477582.03836124649217.7488402052477848.19087232649274.679858617
2478061.68219136649317.3781224272478417.50105644649354.383284395
#Sta/Elev= 30
       0 1867.14    55.5 1847.75    94.8  1836.3   107.1 1835.72   119.3 1832.38
   164.3 1824.17   242.1  1825.5   291.1  1823.7   348.2 1823.54   352.7 1822.93
   359.5 1819.72   366.9 1817.93  380.67 1819.72   384.9 1821.05     389 1823.56
   401.2 1834.07   417.9 1847.01   462.4 1878.14  473.431884.638   489.3 1892.64
   535.2  1912.2   551.3 1919.94  576.811929.571   594.2 1935.91   619.7 1943.58
   667.9 1955.85     680 1957.89   736.2 1971.56   824.8 1988.07   847.6 1989.22
#Mann= 5 ,-1 , 0
       0      .1       0   359.5    .045       0  380.67      .1       0
  473.43     .12       0  576.81      .1       0
Bank Sta=359.5,380.67
XS Rating Curve= 0 ,0
Exp/Cntr(USF)=0,0
Exp/Cntr=0.3,0.1

Type RM Length L Ch R = 1 ,1054    ,247.4,246,243.3
XS GIS Cut Line= 4
2477530.80044467649438.3565365532477731.48228457649500.980656807
2477946.39687908649589.2237353462478263.78730673649670.350436584
#Sta/Elev= 30
       0 1858.94    89.8 1840.12    96.3 1838.21   108.9 1837.38     155 1828.55
   182.4 1822.46   201.1 1816.86   287.3 1815.95   291.6 1815.56  300.341813.755
   313.2 1812.43   321.5 1812.78  326.981813.755   343.5 1817.42   349.1 1817.57
   360.8  1816.7   367.5 1817.85   378.1  1822.8     395 1833.52   416.5 1843.89
   455.3 1859.93   481.6 1872.03   551.6 1900.16   566.8 1905.34     637 1924.89
  672.731932.721   690.6 1936.14     736 1942.37   752.6 1943.57   770.1 1943.95
#Mann= 4 ,-1 , 0
       0      .1       0  300.34    .045       0  326.98      .1       0
  672.73     .12       0
#XS Ineff= 2 , 0
           279.9 1816.25  347.23         1817.57
Permanent Ineff=
       F       F
Bank Sta=300.34,326.98
XS Rating Curve= 0 ,0
Exp/Cntr(USF)=0,0
Exp/Cntr=0.3,0.1