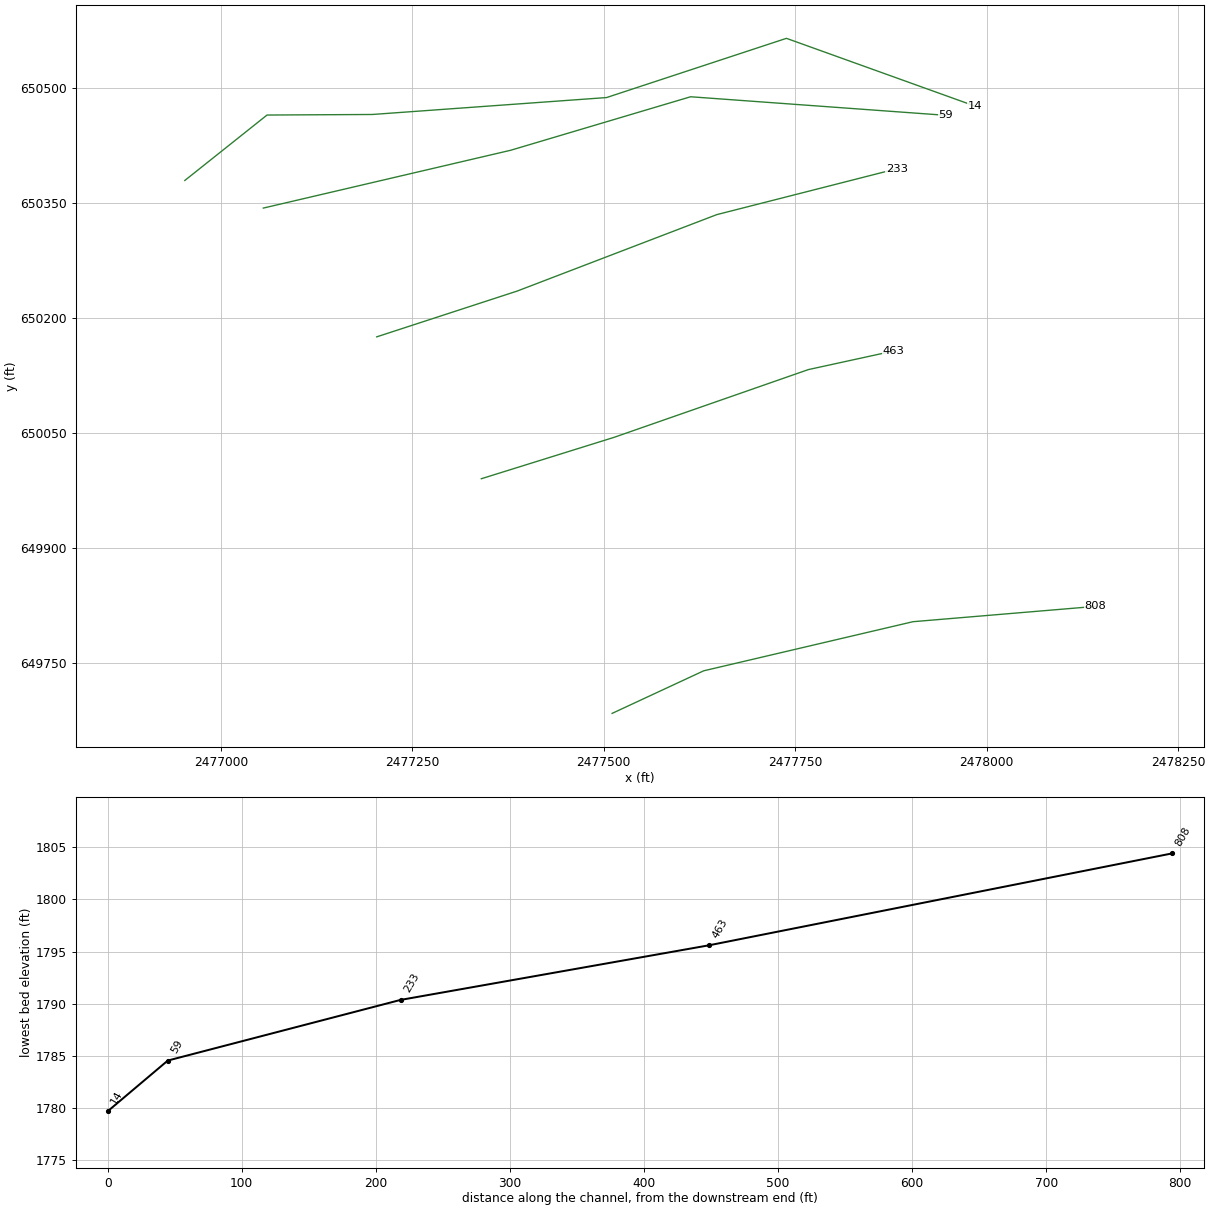
HEC-RAS study JOHNSONRN.prj: JOHNSONRN

--- JOHNSONRN.g01 (geometry) --- (continued)

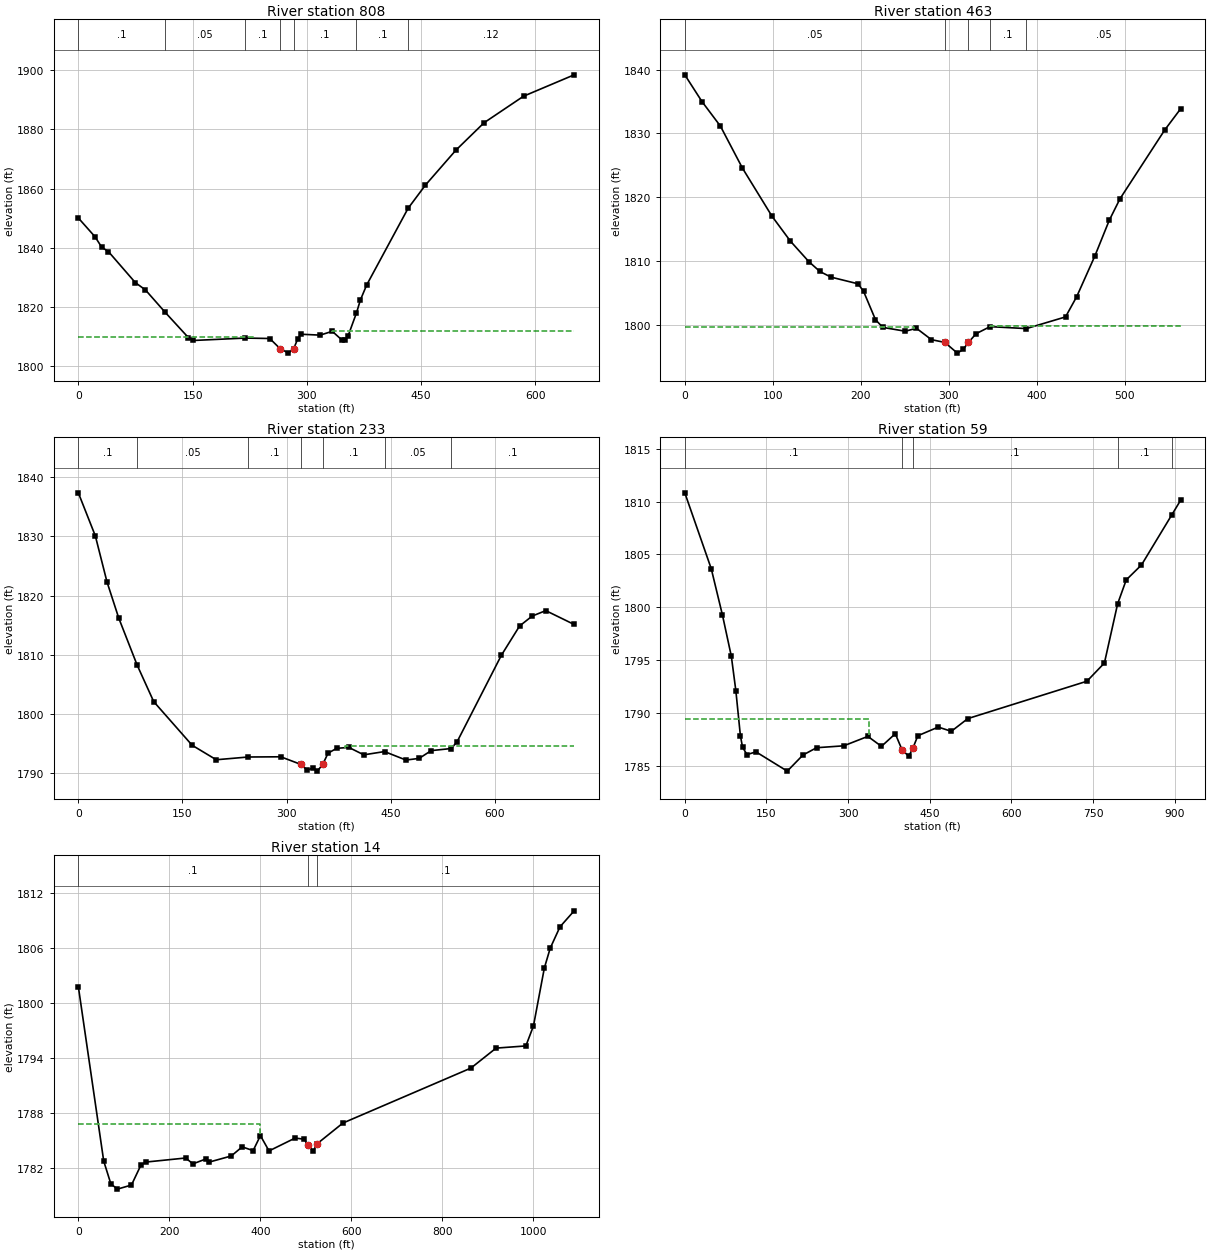
Type RM Length L Ch R = 1 ,808     ,344.3,345.5,345.4
XS GIS Cut Line= 4
2477510.87458823649684.5831911872477630.42972689649740.090934139
2477903.69861527649804.1383298532478141.38561714649824.064186297
#Sta/Elev= 30
       0 1850.07    21.9 1843.73    30.7 1840.19    39.5 1838.72    74.8 1828.25
    88.1 1825.77  113.721818.292   144.4 1809.69     151 1808.69  219.061809.508
   251.3 1809.36  264.761805.973   275.9 1804.42  282.821805.974   288.3 1809.36
   292.4  1810.8   317.5  1810.5   333.4 1811.79   345.8 1808.92   349.9 1808.81
   354.1 1810.18  365.191818.007   370.4 1822.42   378.6 1827.44  432.891853.303
   455.7 1861.17   495.8 1872.99   532.7 1882.23   584.5 1891.19     651 1898.42
#Mann= 7 ,-1 , 0
       0      .1       0  113.72     .05       0  219.06      .1       0
  264.76    .045       0  282.82      .1       0  365.19      .1       0
  432.89     .12       0
#XS Ineff= 2 , 0
          231.47 1809.82  332.52         1811.81
Permanent Ineff=
       F       F
Bank Sta=264.76,282.82
XS Rating Curve= 0 ,0
Exp/Cntr(USF)=0,0
Exp/Cntr=0.3,0.1

Type RM Length L Ch R = 1 ,463     ,231.1,230,231.2
XS GIS Cut Line= 4
2477340.08153299649990.5874151532477513.72113915650044.671882645
2477767.06417108650132.9149611842477878.07965699650157.110644009
#Sta/Elev= 30
       0 1839.17    19.5 1834.99    40.5 1831.14    65.6 1824.55    99.1 1817.04
   120.1 1813.13     141 1809.93   153.6 1808.38   166.2  1807.5     197 1806.45
   203.3 1805.26   216.8 1800.84   225.1 1799.63   250.7 1799.03   263.4 1799.49
   280.4 1797.71  295.681797.276   309.9  1795.6   316.4 1796.17  322.511797.278
   331.2 1798.64  347.071799.747  388.351799.442   432.9 1801.27   445.6 1804.44
   466.2 1810.79   482.6 1816.39   494.8 1819.76   545.6 1830.52563.7606 1833.85
#Mann= 5 ,-1 , 0
       0     .05       0  295.68    .045       0  322.51     .05       0
  347.07      .1       0  388.35     .05       0
#XS Ineff= 2 , 0
          260.73 1799.69  346.56         1799.78
Permanent Ineff=
       F       F
Bank Sta=295.68,322.51
XS Rating Curve= 0 ,0
Exp/Cntr(USF)=0,0
Exp/Cntr=0.3,0.1

Type RM Length L Ch R = 1 ,233     ,173.4,173.6,174.9
XS GIS Cut Line= 4
 2477203.4470888650175.6132249932477387.04962318650235.390794327
2477647.50903242650335.0200765482477882.34948337650394.797645881
#Sta/Elev= 30
       0 1837.33    24.5 1830.06    41.3 1822.29    58.2  1816.2   84.661808.274
   108.6 1802.09   163.9 1794.73   198.7 1792.28  244.561792.743   291.6 1792.78
  320.631791.493   329.8  1790.5   338.1 1790.92   344.3 1790.36  352.081791.494
   359.7 1793.38   372.1 1794.21   389.8 1794.36   411.2 1793.11  441.07 1793.66
     472 1792.23     491 1792.51   508.3 1793.82  537.051794.174   545.5 1795.28
   609.4 1809.91   635.7 1814.86   653.8 1816.53   673.4 1817.45714.2817 1815.11
#Mann= 7 ,-1 , 0
       0      .1       0   84.66     .05       0  244.56      .1       0
  320.63    .045       0  352.08      .1       0  441.07     .05       0
  537.05      .1       0
#XS Ineff= 2 , 0
                          384.35         1794.52
Permanent Ineff=
       F       F
Bank Sta=320.63,352.08
XS Rating Curve= 0 ,0
Exp/Cntr(USF)=0,0
Exp/Cntr=0.3,0.1

Type RM Length L Ch R = 1 ,59      ,49,44.8,39.5
XS GIS Cut Line= 4
2477055.42644093 650343.559729312477378.50997042650418.993328706
2477613.35042137650488.7338262622477946.39687908650464.538143436
#Sta/Elev= 30
       0 1810.82    48.6 1803.65    69.1 1799.29    85.5 1795.38    93.8 1792.12
   102.1 1787.89   106.1 1786.79   114.3  1786.1   130.7 1786.36   188.2 1784.54
     217 1786.06     242 1786.75   291.9 1786.93   336.2 1787.82   361.2 1786.88
   386.6 1788.07   398.8 1786.58   411.3 1785.94   418.7 1786.68     428 1787.88
   465.5  1788.7   489.5  1788.3   519.8  1789.5   738.6 1793.03   770.7 1794.75
  794.931800.331   810.8  1802.6   838.8 1804.01  894.641808.754910.6741 1810.12
#Mann= 5 ,-1 , 0
       0      .1       0   398.8    .045       0   418.7      .1       0
  794.93      .1       0  894.64     .05       0
#XS Ineff= 2 , 0
          338.73 1789.43
Permanent Ineff=
       F       F
Bank Sta=398.8,418.7
XS Rating Curve= 0 ,0
Exp/Cntr(USF)=0,0
Exp/Cntr=0.3,0.1

Type RM Length L Ch R = 1 ,14      ,14,14,14
XS GIS Cut Line= 6
2476952.90789776 650379.567757482477060.27164507650464.898248713
2477197.83797733650465.6322461582477503.60923627650487.698213298
2477738.45417226650564.9290982872477984.33209182650476.665229728
#Sta/Elev= 30
       0 1801.79   55.831782.734  71.4691780.259  85.8371779.677 116.8091780.123
 137.5331782.293 148.0061782.629 236.0081783.075 252.0081782.434 280.0211782.965
 288.0421782.633 336.1671783.295 360.2291784.291 384.291 1783.88 400.3331785.518
 419.2641783.848 476.5311785.249 496.5831785.131 504.6031784.505 516.635 1783.81
 523.9971784.588 581.667 1786.89 863.1941792.892 918.4431795.071 983.9441795.309
1000.6651797.4951024.5991803.817 1037.441805.9731058.9991808.3141090.1261810.058
#Mann= 3 , 0 , 0
       0      .1       0 504.603    .045       0 523.997      .1       0
#XS Ineff= 2 , 0
          399.43 1786.79
Permanent Ineff=
       F       F
Bank Sta=504.603,523.997
XS Rating Curve= 0 ,0
Exp/Cntr(USF)=0,0
Exp/Cntr=0.3,0.1
LCMann Table=0

Chan Stop Cuts=-1
Use User Specified Reach Order=0
Composite Channel Slope=5